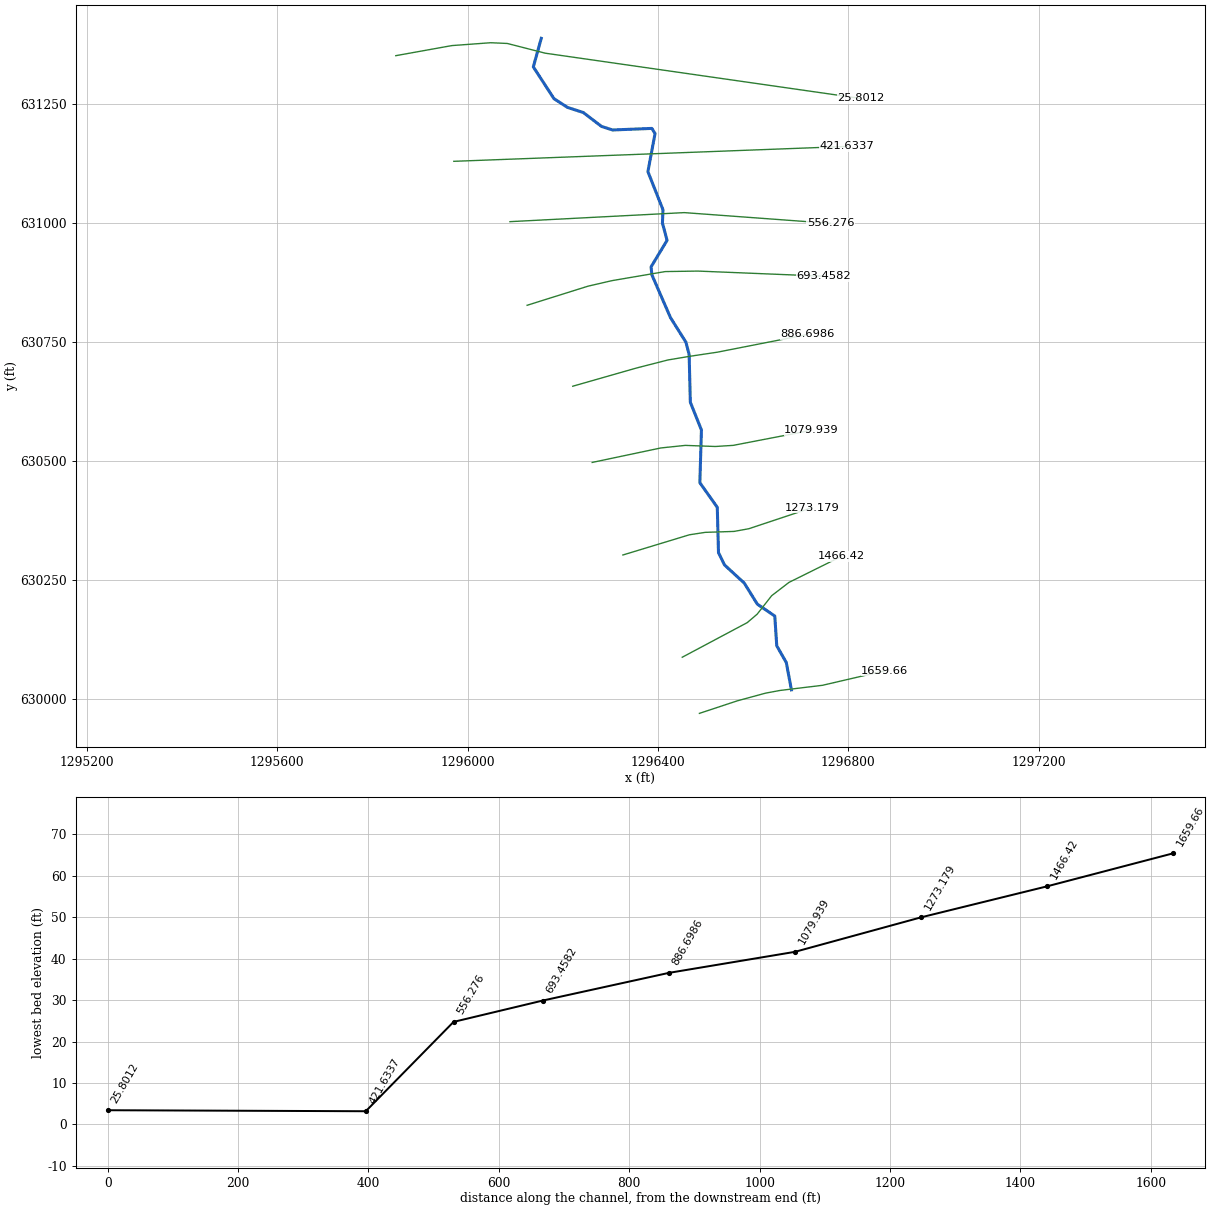
--- 793_ras.prj (project) ---

Proj Title=793
Current Plan=p01
Default Exp/Contr=0.3,0.1
English Units
Geom File=g01
Flow File=f01
Plan File=p01
Y Axis Title=Elevation
X Axis Title(PF)=Main Channel Distance
X Axis Title(XS)=Station
BEGIN DESCRIPTION:
RFD model 793 exported to HEC-RAS
END DESCRIPTION:

--- 793_ras.p01 (plan) ---

Plan Title=Plan 01
Program Version=4.10
Short Identifier=Plan 01
Geom File=g01
Flow File=f01
Subcritical Flow
Calc Critical at every XS
Secant Critical Depth

--- 793_ras.f01 (steady flow) ---

Flow Title=Flow 01
Program Version=5.01
Number of Profiles= 5
Profile Names=10yr,25yr,50yr,100yr,500yr
River Rch & RM=793,9, 1659.66
  366.08  433.68  516.21  546.75  635.39
River Rch & RM=793,9,1273.179
   375.4  446.37  531.75  565.32  660.11
River Rch & RM=793,9,1079.939
  420.55  508.42  607.97  657.29  784.23
River Rch & RM=793,9,886.6986
   451.8  551.95  661.59  722.89   874.3
River Rch & RM=793,9,693.4582
  480.05  591.68  710.64  783.48  958.55
River Rch & RM=793,9, 556.276
   481.3  593.45  712.83   786.2  962.34
River Rch & RM=793,9,421.6337
  491.75  608.25  731.12  808.93  994.22
River Rch & RM=793,9, 25.8012
   527.8  659.62  794.74  888.58 1106.86
Boundary for River Rch & Prof#=793,9,1
Up Type= 0
Dn Type= 2
Boundary for River Rch & Prof#=793,9,2
Up Type= 0
Dn Type= 2
Boundary for River Rch & Prof#=793,9,2
Up Type= 0
Dn Type= 2
Boundary for River Rch & Prof#=793,9,2
Up Type= 0
Dn Type= 2
Boundary for River Rch & Prof#=793,9,2
Up Type= 0
Dn Type= 2

--- 793_ras.g01 (geometry) ---

Geom Title=793
Program Version=4.10

River Reach=793,9
Reach XY= 30
1296680.65183008630018.9940556141296669.81850162630076.494038865
1296649.81850857 630111.494029031296645.65184495630173.994010583
1296608.98518986630198.9940042791296581.48519924630243.160658628
1296539.81854606630281.4939817941296527.31855047630307.327307835
1296524.81855401630402.3272797171296488.15189973630453.993932173
 1296491.4852353 630564.827232421296468.15191057630623.160549179
 1296465.6519143 630723.160519571296458.98525032630748.993845388
1296426.48526147630800.6604976951296387.31860897 630890.66047211
1296385.65194327630907.3271339091296419.27425414630963.132667407
 1296409.5520319630999.2437785271296410.65193948 631027.32709755
1296378.98528451631107.3270747071296393.98528242631187.327050507
1296387.31861809 631198.160380871296304.81864229631194.827050939
1296281.48531607631202.3270494041296243.15199491631231.493708536
1296209.81867176631242.327039599 1296181.4853473631260.660368368
1296138.15202868631327.3270165321296154.81869221631387.326998219

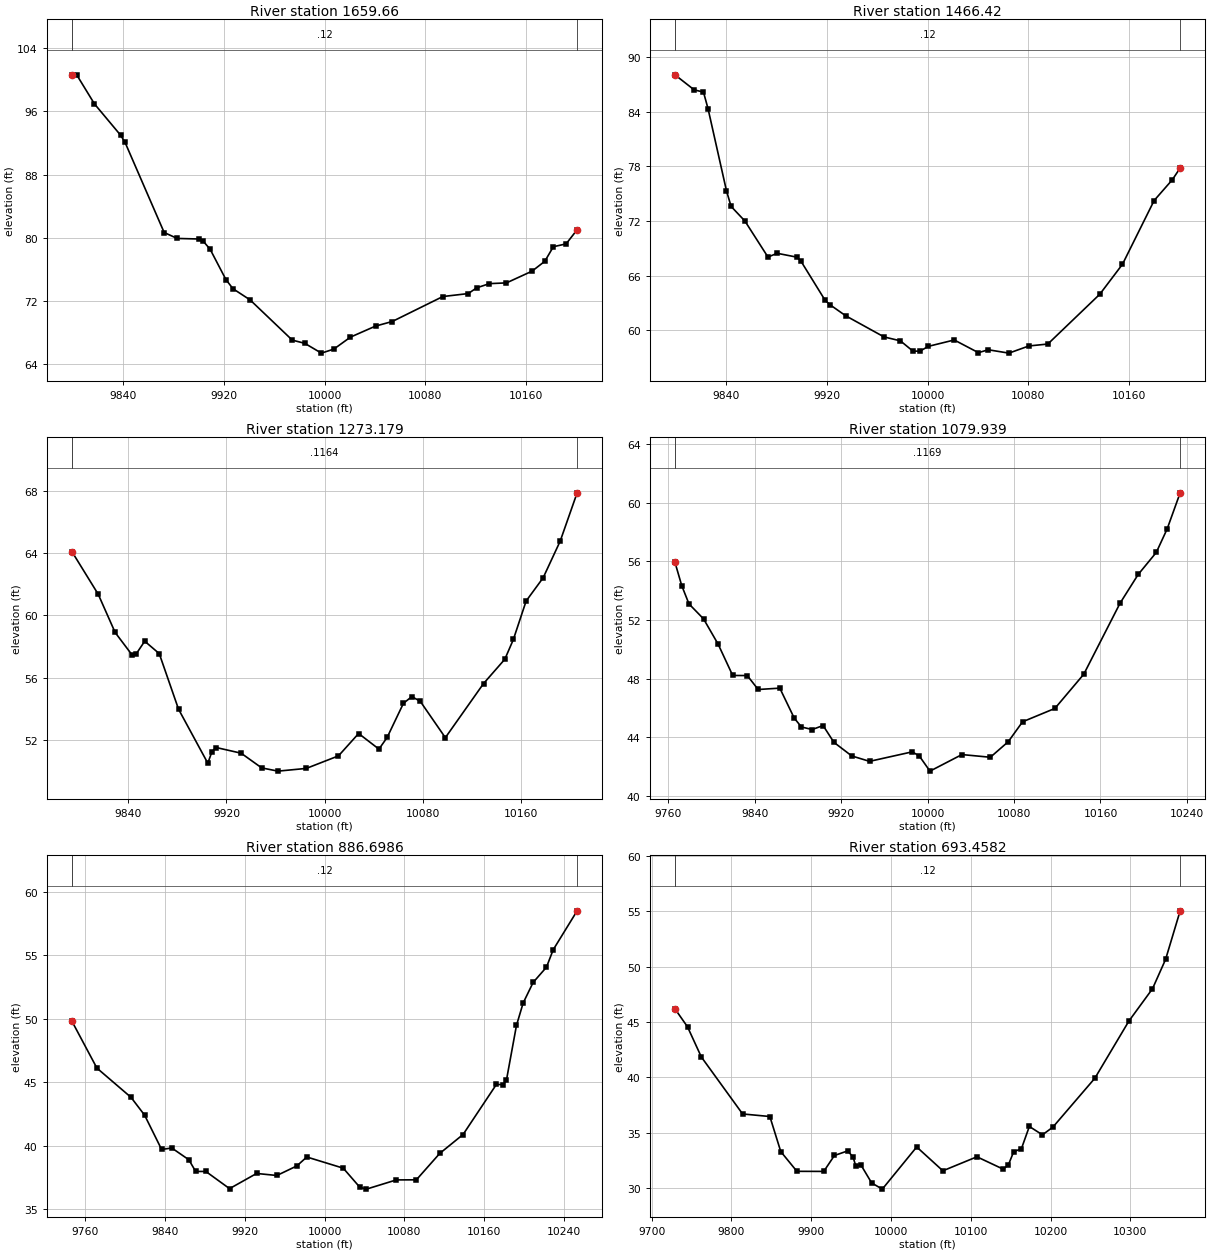
Type RM Length L Ch R = 1 , 1659.66,193.240400,193.240400,193.240400
XS GIS Cut Line= 6
1296487.25084974 629969.556261481296566.78941703629995.864695872
1296626.30373926 630012.038505121296656.83290305630017.730835906
1296746.09911214630028.5486587931296876.88395675630058.960939097
#Sta/Elev= 30
9799.625100.59269803.687100.51969817.50996.916549838.24392.964559841.69992.08214
  9872.880.670989883.16779.92289 9900.1779.853769903.56979.618199909.28978.54667
9921.79974.723929927.36873.571859940.967 72.15919974.41767.078099984.32666.67402
9997.51165.4348910007.3965.9425910020.5667.4549510040.4568.8494710053.7469.42979
10093.8872.5848310114.0172.9582710120.7273.6846210130.82 74.214110144.34 74.3082
10164.6275.7891810174.7677.0387810181.5278.8770110191.6579.2348310200.3981.02413
#Mann= 3 , 0 , 0
9799.625    0.12       09799.625    0.12       010200.39    0.12       0
#XS Ineff= 2 , 0
       09948.124        10036.08       0
Bank Sta=9799.625,10200.39
Exp/Cntr=0.3,0.1

Type RM Length L Ch R = 1 , 1466.42,193.240400,193.240400,193.240400
XS GIS Cut Line= 6
1296451.12513284630087.4402530961296587.67336766630160.092826928
1296608.51214482630177.7818052011296639.06979399630216.664076163
1296675.49968415630244.6566449291296785.54850042630299.212065639
#Sta/Elev= 30
 9799.7288.060019815.01586.403069822.32286.166379825.97584.329189840.58975.30439
9844.243 73.59929855.20371.98986 9873.4768.033199880.77768.445499896.231 68.0276
9899.59867.588079918.61763.318489922.421 62.81439935.131 61.57869965.54659.25338
9978.456 58.82699988.46857.691429993.99357.6908310000.6658.2195210021.1958.92017
10040.3657.5245710048.1457.8439610064.5557.4742810080.3658.26163 10095.458.47307
10136.6463.9526110154.5967.2402610179.7174.2476610194.0676.5183810200.3377.82112
#Mann= 3 , 0 , 0
 9799.72    0.12       0 9799.72    0.12       010200.33    0.12       0
#XS Ineff= 2 , 0
       09970.429        10043.73       0
Bank Sta=9799.72,10200.33
Exp/Cntr=0.3,0.1

Type RM Length L Ch R = 1 ,1273.179,193.240400,193.240400,193.240400
XS GIS Cut Line= 6
1296326.36663235630302.1980365811296466.08972954630344.608181928
1296499.50721991630349.7476911611296560.10191173630351.720706382
1296591.33833935630357.4167910291296723.95707869630401.553387969
#Sta/Elev= 30
 9793.9764.084599815.39961.350249829.19558.896379842.99157.45611 9846.4457.52345
9853.33858.333499865.20557.535919880.93153.966829904.802 50.50079908.19851.24547
9911.59451.508169931.96951.143699948.74850.199589962.026  49.9929985.13450.16599
10011.3950.9724810027.8152.4077310044.3851.4049210051.0552.1512910064.3954.35025
10071.1854.7752310078.03 54.480210098.5552.14059 10129.755.6154510147.07 57.1773
10154.0258.4440310164.4460.9150710178.3362.4072910192.23 64.761910206.0367.86023
#Mann= 3 , 0 , 0
 9793.97  0.1164       0 9793.97  0.1164       010206.03  0.1164       0
#XS Ineff= 2 , 0
       09939.336        10026.99       0
Bank Sta=9793.97,10206.03
Exp/Cntr=0.3,0.1

Type RM Length L Ch R = 1 ,1079.939,193.240400,193.240400,193.240400
XS GIS Cut Line= 6
1296261.96237187630496.6071756541296406.31125652630527.044581676
1296457.69253379630532.4158070641296520.78411952630530.066303001
1296558.27792557630532.444298112 1296722.6822304630564.100472905
#Sta/Elev= 30
  9766.355.942459772.58654.34652 9779.2653.101489792.74952.077399806.237 50.3497
9819.72548.209129833.21348.203439843.29147.25077 9863.3147.343599876.65545.29644
9883.32844.688359893.33744.516189903.34644.788559913.35643.641889929.85542.71077
9946.34842.34064 9985.8342.990559992.39442.7054410002.2541.6726110031.8142.80406
10058.1142.6205410074.6343.6811610087.9245.0436710117.8245.9574310144.5548.29502
10178.0953.1446210194.8655.1100710211.6356.6166310221.6958.2229210233.7260.69067
#Mann= 3 , 0 , 0
  9766.3  0.1169       0  9766.3  0.1169       010233.72  0.1169       0
#XS Ineff= 2 , 0
       09919.112        10044.42       0
Bank Sta=9766.3,10233.72
Exp/Cntr=0.3,0.1

Type RM Length L Ch R = 1 ,886.6986,193.240400,193.240400,193.240400
XS GIS Cut Line= 6
1296220.97915358630656.6543617171296354.70356589630694.826107409
1296421.04230914630711.7967985821296464.97932838630719.189954214
1296525.37878553630728.2347011751296714.80112025630765.407392102
#Sta/Elev= 30
9746.90449.818059771.93146.12911 9806.0543.830859819.69742.427529836.75739.72496
9846.99239.838219864.05238.913759870.87637.992779881.11137.991479904.85336.63923
9931.94537.834149952.26437.674679972.26438.427139982.24439.1306510018.7738.25058
10035.3736.74892   1004236.6010510071.9637.3269510092.0237.3334310115.4239.40908
10138.8340.9010710172.2644.8485810178.9544.8228710182.2945.1793910192.3249.48332
10199.0151.2486710209.04 52.871810222.4154.07402 10229.155.4398810253.1158.50784
#Mann= 3 , 0 , 0
9746.904    0.12       09746.904    0.12       010253.11    0.12       0
#XS Ineff= 2 , 0
       09886.272        10065.41       0
Bank Sta=9746.904,10253.11
Exp/Cntr=0.3,0.1

Type RM Length L Ch R = 1 ,693.4582,137.182200,137.182200,137.182200
XS GIS Cut Line= 6
1296125.12530237630826.6648296861296252.97630668630866.753250048
1296303.10177419630878.3483401691296415.39466053630897.467861861
1296484.18612584630898.504949734 1296748.8315458630887.704426676
#Sta/Elev= 30
9729.25846.192729745.00344.56914  9762.341.852019814.01936.709579848.18136.47767
9861.84733.314689882.07231.532739915.73631.524329929.07132.960369945.73933.37596
9952.40632.82237 9955.7432.037449962.40732.094779975.74230.483999989.07629.92605
10032.1833.7295510064.9931.5803110107.6632.8426310140.4931.7312410147.0632.11372
10153.6333.2863410163.4833.5889510173.3335.5805110189.7434.8247110202.8835.52435
10255.42  39.932 10298.145.0945110327.65 48.006710344.0750.6582310362.3155.03736
#Mann= 3 , 0 , 0
9729.258    0.12       09729.258    0.12       010362.31    0.12       0
#XS Ineff= 2 , 0
       09961.032        10047.26       0
Bank Sta=9729.258,10362.31
Exp/Cntr=0.3,0.1

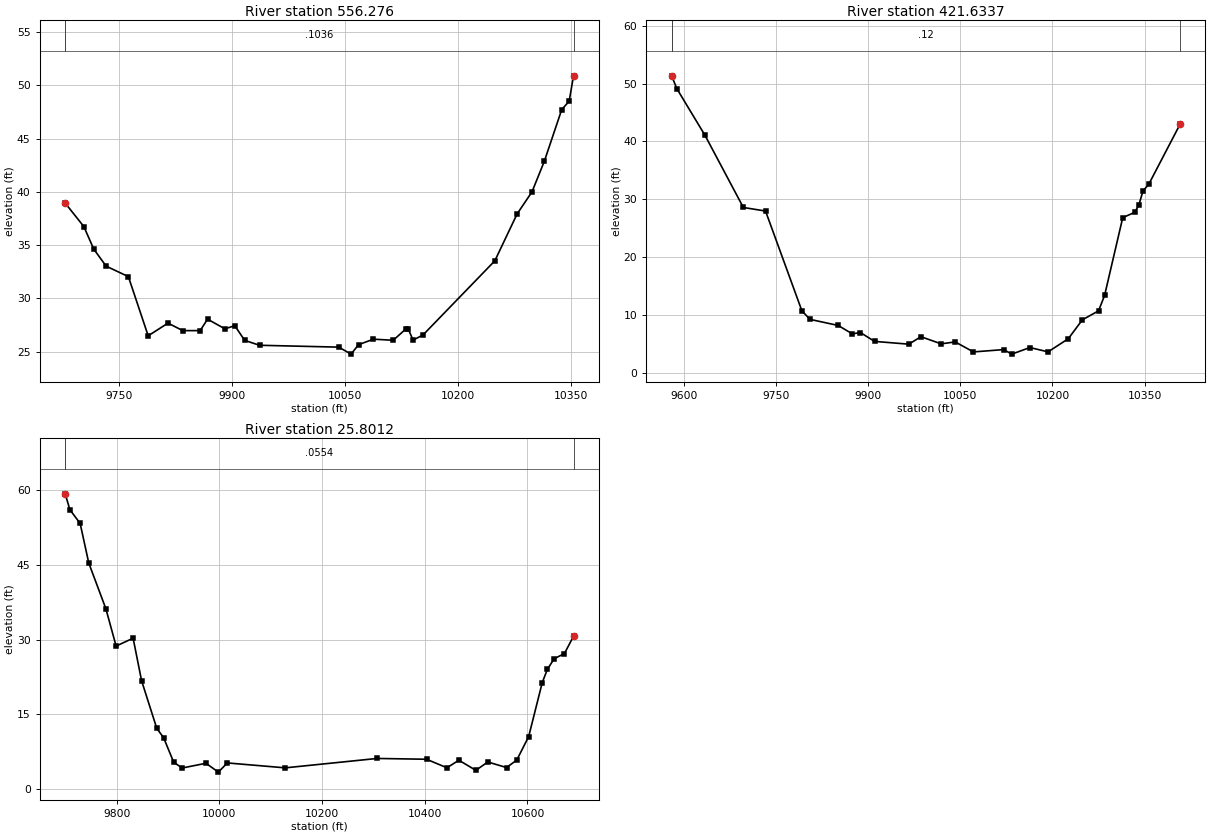
Type RM Length L Ch R = 1 , 556.276,134.642300,134.642300,134.642300
XS GIS Cut Line= 3
1296089.10932356631002.2877600041296455.34196246631021.292389616
1296762.63362911630998.722945198
#Sta/Elev= 30
9678.35338.937059703.08836.737539716.22934.627379732.65533.023629762.22332.03844
9788.50426.484879814.78627.672159834.49826.970749857.49526.96952 9867.3528.04334
9890.34727.139879903.48827.430889916.62926.053229936.34125.5950210041.4725.41973
10057.9124.7638710067.7825.6508110087.5226.1660610113.8426.0651310130.2827.10571
10133.5727.1502410140.1526.0834210153.3126.5575210248.7133.5232410278.3237.92886
10298.0639.9969710314.5142.8839210337.5347.72043 10347.448.50548 10353.250.88761
#Mann= 3 , 0 , 0
9678.353  0.1036       09678.353  0.1036       0 10353.2  0.1036       0
#XS Ineff= 2 , 0
       09972.663        10032.83       0
Bank Sta=9678.353,10353.2
Exp/Cntr=0.3,0.1

Type RM Length L Ch R = 1 ,421.6337,395.832500,395.832500,395.832500
XS GIS Cut Line= 2
1295971.05376804631129.0238711241296797.44265693631160.273871124
#Sta/Elev= 30
9580.55851.334149588.80749.138629634.77241.040189697.15228.564269733.26727.94611
9792.36410.700579805.4979.2122379851.4628.1547589874.4446.7039529887.5776.934373
9910.5595.4014859966.3734.9185039986.0726.211897 10018.94.97772410041.895.308041
10071.433.57941710120.683.98116510133.813.19766410163.364.33499710192.913.589681
10225.745.85400310248.739.13420810274.9910.6810810284.8413.3393610314.3926.80804
10334.0927.7303510340.6629.0180310347.2231.3769810357.0732.6478910407.5442.94157
#Mann= 3 , 0 , 0
9580.558    0.12       09580.558    0.12       010407.54    0.12       0
#XS Ineff= 2 , 0
       09929.261        10042.34       0
Bank Sta=9580.558,10407.54
Exp/Cntr=0.3,0.1

Type RM Length L Ch R = 1 , 25.8012,0.000000,0.000000,0.000000
XS GIS Cut Line= 6
 1295849.0477986631350.9042100311295966.85214701631372.077243581
1296048.66427737 631378.108052821296083.48144686631376.557041064
1296162.95534918631356.176525101 1296826.9565458631260.968315542
#Sta/Elev= 30
9699.878 59.24129708.91156.066499728.98253.303869745.70845.383449779.06136.19642
9798.98528.71656 9832.1130.294839848.60521.765789878.21612.195319891.35110.37513
9911.0545.4413639927.4744.2658579974.0285.2157739998.0773.44210410015.455.286143
10128.294.30010210307.27 6.1833410403.396.02481610443.164.31260610466.365.827334
 10499.53.802582 10522.75.47680110559.164.36089210579.055.85350310602.2510.55564
10628.7621.4098410638.7124.0554510651.9726.1886910671.8527.2079510689.6430.68683
#Mann= 3 , 0 , 0
9699.878  0.0554       09699.878  0.0554       010689.64  0.0554       0
#XS Ineff= 2 , 0
       09961.436        10046.52       0
Bank Sta=9699.878,10689.64
Exp/Cntr=0.3,0.1